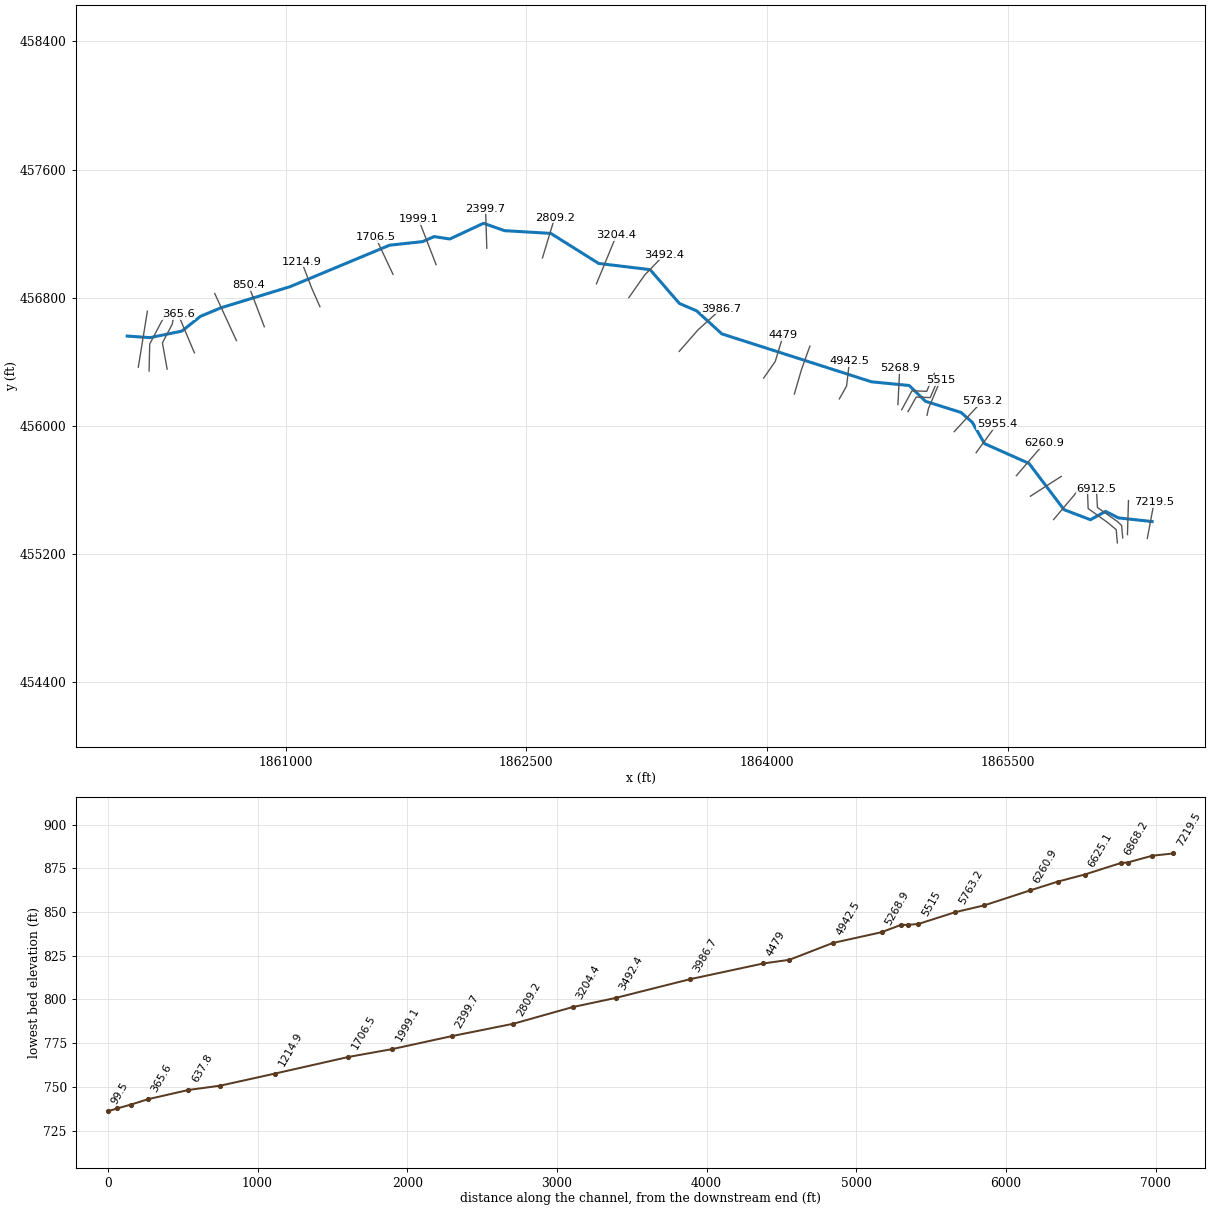
--- FIVEMLEFK1.prj (project) ---

Proj Title=FIVEMLEFK1
Current Plan=p01
Default Exp/Contr=0,0
English Units
Geom File=g01
Flow File=f01
Plan File=p01
BEGIN DESCRIPTION:
END DESCRIPTION:
DSS Export Rating Curves= 0
DSS Export Rating Curve Sorted= 0
DSS Export Volume Flow Curves= 0
DXF OffsetX= 0
DXF OffsetY= 0
DXF ScaleX= 0
DXF ScaleY= 0

--- FIVEMLEFK1.p01 (plan) ---

Plan Title=Floodplain
Program Version=4.00
Geom File=g01
Flow File=f01
K Sum by GR=0
Std Step Tol=0.01
Critical Tol=0.01
Num of Std Step Trials=20
Max Error Tol=0.3
Flow Tol Ratio=0.001
Split Flow NTrial=30
Split Flow Tol=0.02
Split Flow Ratio=0.02
Log Output Level=0
Friction Slope Method=1
Unsteady Friction Slope Method=2
Unsteady Bridges Friction Slope Method=1
Global Log Level=0
CheckData=False
Run HTab=0
Run UNet=0
Run PostProcess=0
UNET Theta=0
UNET Theta Warmup=0
UNET ZTol=0
UNET ZSATol=0
UNET MxIter=0
UNET MaxInSteps=0
UNET DtIC=0
UNET DtMin=0
UNET MaxCRTS=0
UNET WFStab=0
UNET SFStab=0
UNET WFX=0
UNET SFX=0
UNET DSS MLevel=0
UNET DZMax Abort=0
UNET Convert EG Bridges=0
UNET Use Existing IB Tables=0
UNET Froude Limit=0
UNET Froude Power=0
Write IC File=0
Echo Input=False
Echo Output=False
Write Detailed=0

--- FIVEMLEFK1.f01 (steady flow) ---

Flow Title=NFF Regression Equation
Program Version=4.10
Number of Profiles= 1
Profile Names=P100yr
River Rch & RM=FIVEMLEFK1,Main            ,7219.5
829.0608
River Rch & RM=FIVEMLEFK1,Main            ,6625.1
831.8567
River Rch & RM=FIVEMLEFK1,Main            ,6447.8
943.0943
River Rch & RM=FIVEMLEFK1,Main            ,5955.4
952.1741
River Rch & RM=FIVEMLEFK1,Main            ,3492.4
1053.104
River Rch & RM=FIVEMLEFK1,Main            ,365.6
1168.678
Boundary for River Rch & Prof#=FIVEMLEFK1,Main            , 1
Up Type= 0
Dn Type= 3
Dn Slope=0.025
DSS Import GetInterval= 0
DSS Import GetPeak= 0
DSS Import FillOption= 0

--- FIVEMLEFK1.g01 (geometry) ---

Geom Title=USGS 10m DEM
Program Version=4.10

River Reach=FIVEMLEFK1      ,Main
Reach XY= 30
     1866401.274       455402.72     1866190.709      455425.764
     1866111.177       455466.24     1866016.892      455414.088
     1865852.014      455476.916     1865634.132      455765.451
     1865356.514       455889.35     1865280.038        456022.5
     1865210.049      456083.954     1864988.472      456153.602
      1864886.97      456252.106     1864651.343      456275.394
     1863718.956      456574.522     1863562.497      456717.721
     1863454.302      456764.394     1863271.855       456975.48
     1862951.106      457014.201      1862652.52      457201.798
     1862364.396      457218.919     1862233.395      457265.061
     1862023.369      457166.943     1861925.084       457181.84
     1861853.651      457150.501     1861647.775      457128.164
     1861026.991      456869.002     1860595.568      456737.057
     1860468.297      456683.819     1860353.132      456591.776
     1860154.413      456551.016     1860012.321       456560.73

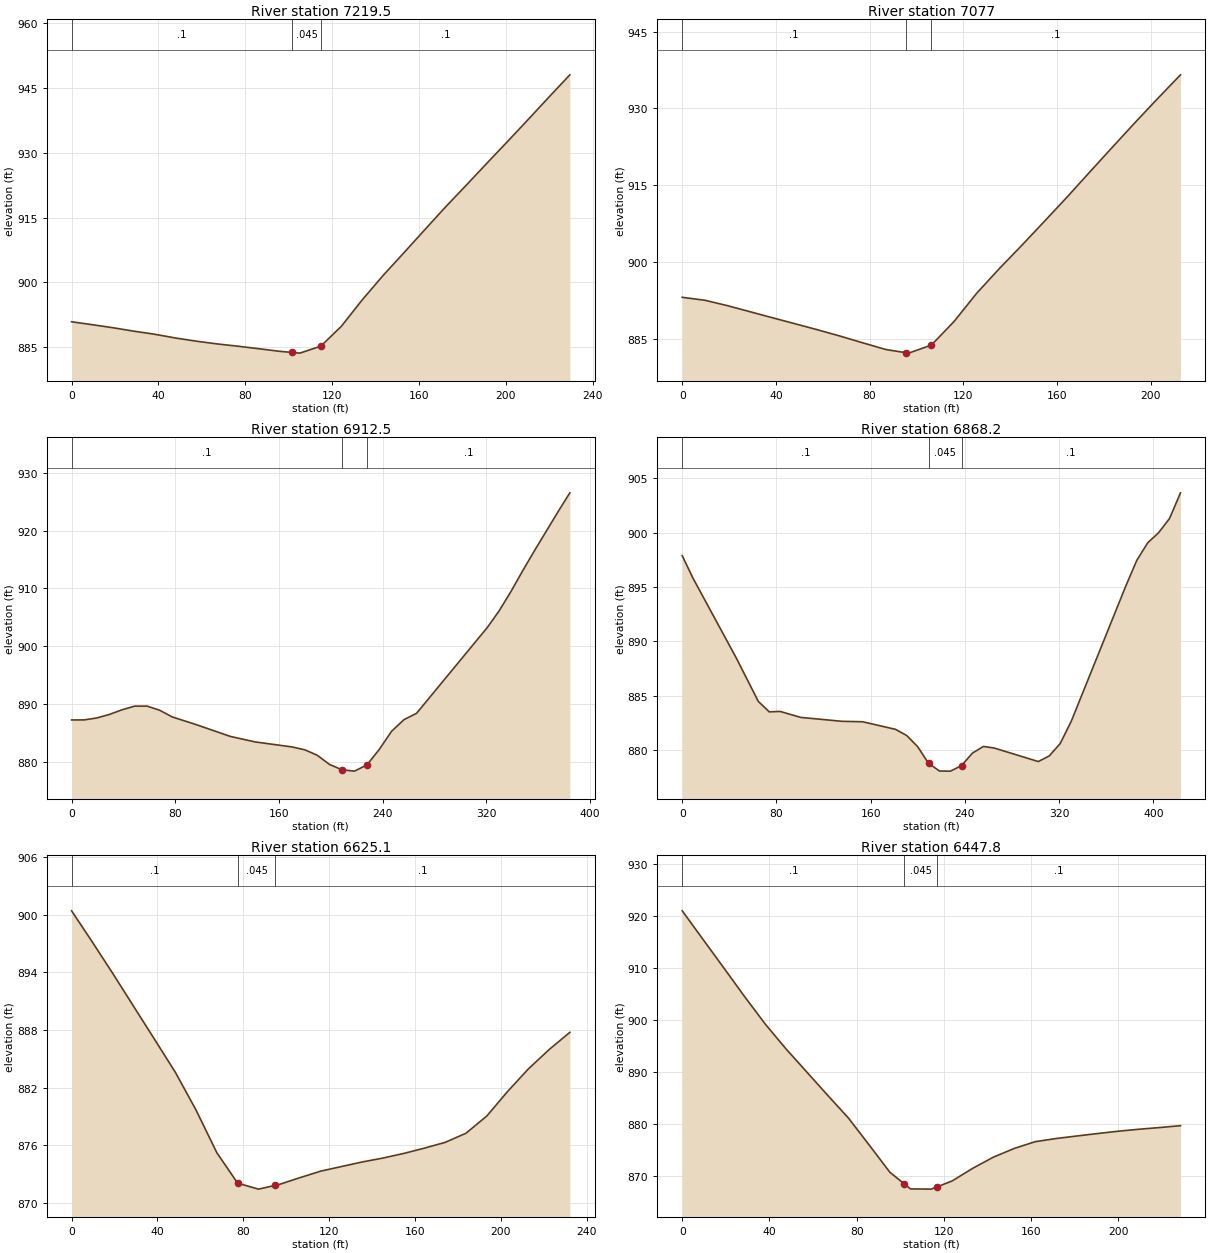
Type RM Length L Ch R = 1 ,7219.5  ,138.9,142.4,145.9
XS GIS Cut Line= 2
     1866371.326      455297.203     1866413.575      455522.647
#Sta/Elev= 27
       0  890.84     9.6  890.16    19.1  889.45    28.7  888.66    38.2  887.95
    47.8  887.08    57.3  886.35    66.9  885.71    76.5  885.18      86   884.6
    95.6     884   101.7  883.72   105.1  883.57   114.7  885.17   116.7  886.14
   124.2  889.79   133.8  895.91   143.4  901.56   152.9  906.78   162.5  912.11
     172  917.36   181.6  922.44   191.1  927.53   200.7  932.62   210.3  937.77
   219.8  942.93   229.4  948.08
#Mann= 3 , 0 , 0
       0      .1       0   101.7    .045       0   114.7      .1       0
Bank Sta=101.7,114.7
XS Rating Curve= 0 ,0
Exp/Cntr=0.3,0.1

Type RM Length L Ch R = 1 ,7077    ,67.1,164.5,188.6
XS GIS Cut Line= 2
      1866247.56      455321.067     1866253.967      455533.741
#Sta/Elev= 25
       0  893.13     9.7  892.55    19.3   891.5      29  890.31    38.7  889.12
    48.4  887.94      58  886.76    67.7  885.52    77.4   884.2      87  882.93
    95.4  882.32    96.7  882.23   106.4   883.8   110.4   885.7   116.1  888.41
   125.7  893.89   135.4  898.72   145.1  903.31   154.7  907.97   164.4  912.72
   174.1  917.62   183.8  922.48   193.4  927.25   203.1  931.96   212.8  936.57
#Mann= 3 , 0 , 0
       0      .1       0    95.4    .045       0   106.4      .1       0
Bank Sta=95.4,106.4
XS Rating Curve= 0 ,0
Exp/Cntr=0.3,0.1

Type RM Length L Ch R = 1 ,6912.5  ,118.9,44.3,41.9
XS GIS Cut Line= 5
     1866218.187      455300.461     1866211.202      455377.845
     1866185.999      455402.388     1866060.478      455490.409
     1866054.057      455608.558
#Sta/Elev= 30
       0  887.21     9.7  887.22    19.4  887.55    29.1  888.16    38.8  888.96
    48.6   889.6    58.3  889.61      68  888.89    77.7  887.73    95.3  886.47
   122.5  884.36   141.6  883.41   170.4  882.53     180  882.04   189.5  881.11
   199.1   879.5   208.7  878.58   218.3  878.35   227.9  879.42   237.4   882.1
     247  885.27   256.6  887.28   266.2  888.36   320.8  903.22   329.9  906.09
     339  909.43   348.1  913.04   357.2  916.52   375.4  923.27   384.5  926.54
#Mann= 3 , 0 , 0
       0      .1       0   208.7    .045       0   227.9      .1       0
Bank Sta=208.7,227.9
XS Rating Curve= 0 ,0
Exp/Cntr=0.3,0.1

Type RM Length L Ch R = 1 ,6868.2  ,280.7,243.1,205.1
XS GIS Cut Line= 5
     1866184.704      455269.388      1866177.47      455352.166
     1866123.686      455397.101     1866002.595      455484.135
     1865997.865      455604.753
#Sta/Elev= 30
       0  897.89     9.2  895.81    46.2  888.42    64.6  884.49    73.9  883.53
    83.1  883.57   100.6  883.02   135.7  882.66   153.2  882.62   181.1  881.92
   190.5  881.36   199.8  880.34   209.1   878.8   218.4  878.09   225.4  878.08
   227.7  878.08   237.1  878.59   246.4  879.74   255.7  880.35     265   880.2
   302.3  878.96   311.6  879.48   320.9  880.62   330.2  882.65   376.6  895.11
   385.9  897.46   395.2  899.08   404.4     900   413.7  901.31     423  903.67
#Mann= 3 , 0 , 0
       0      .1       0   209.1    .045       0   237.1      .1       0
Bank Sta=209.1,237.1
XS Rating Curve= 0 ,0
Exp/Cntr=0.3,0.1

Type RM Length L Ch R = 1 ,6625.1  ,184,177.3,170.5
XS GIS Cut Line= 2
     1865787.431        455415.2     1865936.737      455592.978
#Sta/Elev= 27
       0  900.39     9.7  897.14    19.4  893.81      29  890.43    38.7  887.02
    48.4  883.59      58  879.68    67.7  875.24    77.4  872.08    79.9  871.92
    87.1  871.46    94.9  871.85    96.7  871.94   106.4  872.65   116.1  873.33
   125.8  873.81   135.4  874.28   145.1  874.69   154.8  875.17   164.4  875.72
   174.1  876.32   183.8  877.27   193.5  879.06   203.1  881.59   212.8  883.94
   222.5  885.96   232.2  887.76
#Mann= 3 , 0 , 0
       0      .1       0    77.4    .045       0    94.9      .1       0
Bank Sta=77.4,94.9
XS Rating Curve= 0 ,0
Exp/Cntr=0.3,0.1

Type RM Length L Ch R = 1 ,6447.8  ,180.3,186.9,193.4
XS GIS Cut Line= 2
     1865642.843      455561.055     1865834.974      455684.705
#Sta/Elev= 27
       0  921.05     9.5  915.57      19   910.1    28.6  904.54    38.1  899.23
    47.6  894.46    57.1  890.02    66.6  885.58    76.2  881.16    85.7  875.98
    95.2  870.72   101.9  868.45   104.7   867.5   114.2  867.46   116.9   867.9
   123.8  869.04   133.3  871.49   142.8  873.64   152.3   875.3   161.8  876.59
   171.4   877.2   180.9  877.69   190.4  878.16   199.9  878.61   209.4  878.99
     219  879.32   228.5  879.68
#Mann= 3 , 0 , 0
       0      .1       0   101.9    .045       0   116.9      .1       0
Bank Sta=101.9,116.9
XS Rating Curve= 0 ,0
Exp/Cntr=0.3,0.1

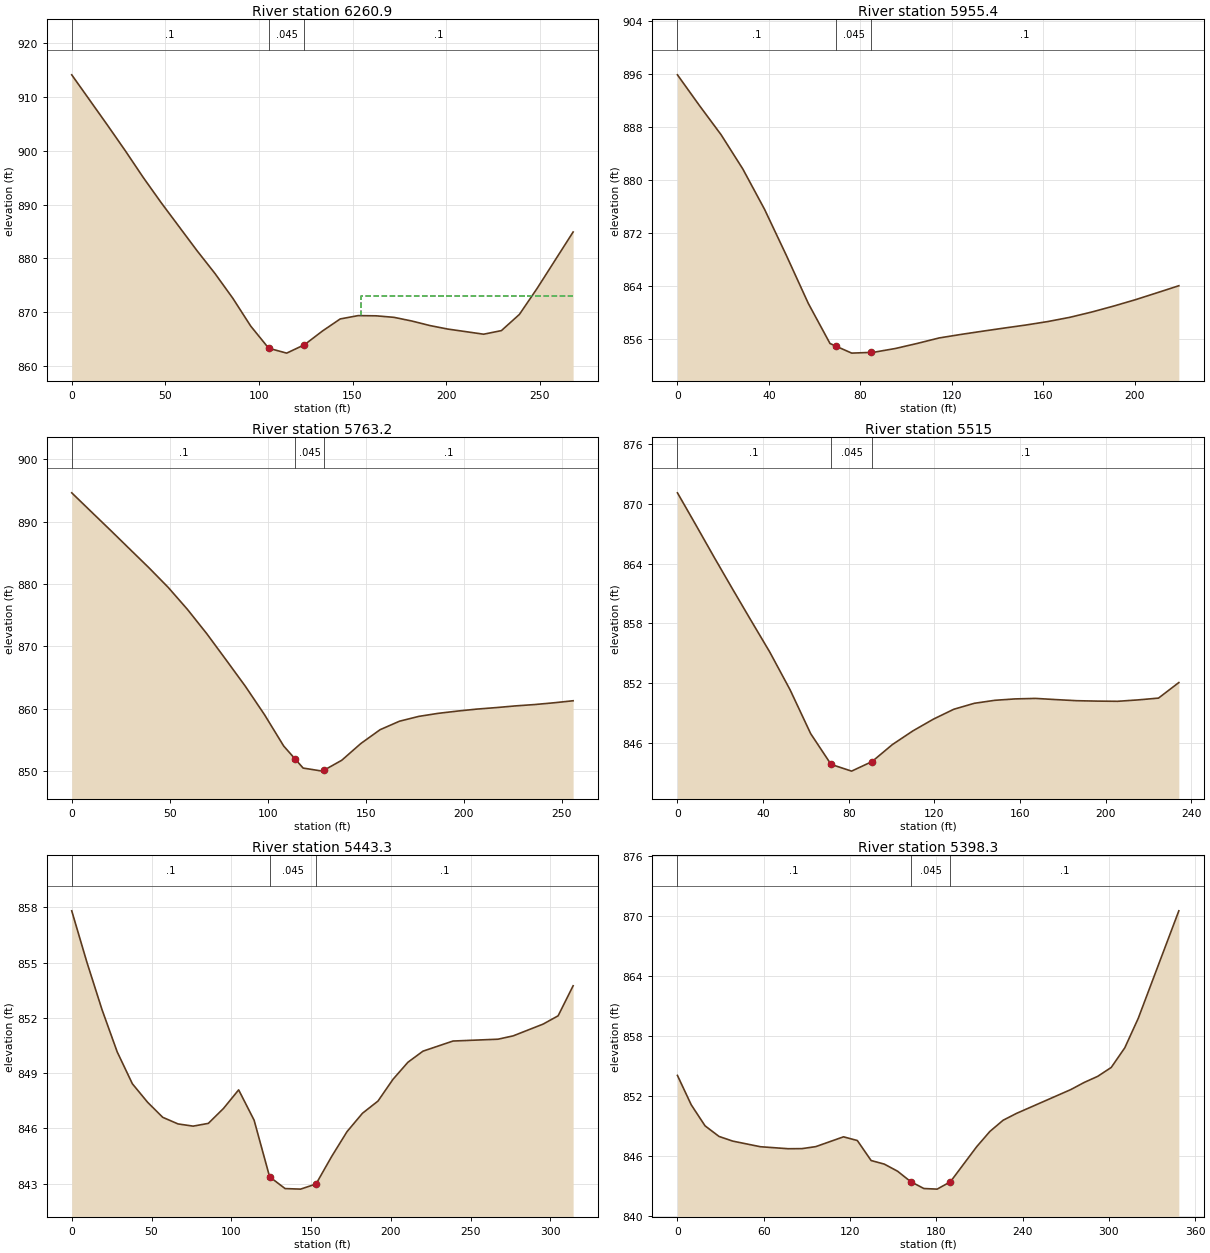
Type RM Length L Ch R = 1 ,6260.9  ,303.7,305.5,307.1
XS GIS Cut Line= 2
     1865555.321      455689.289       1865729.8      455892.414
#Sta/Elev= 25
       0  914.16    19.1  904.79    28.7  899.99    38.2  895.06    47.8  890.36
    66.9  881.45    76.5   877.2    86.1  872.56    95.6  867.41   105.2  863.29
   114.8  862.38   124.3  863.94   133.9  866.49   143.4  868.74     153  869.36
   162.6  869.32   172.1  869.04   181.7  868.35   191.3  867.51   200.8  866.86
     220   865.9   229.5  866.57   239.1  869.58   248.6  874.44   267.8  884.92
#Mann= 3 , 0 , 0
       0      .1       0   105.2    .045       0   124.3      .1       0
#XS Ineff= 2 , 0
                          154.25           873.1
Permanent Ineff=
       F       F
Bank Sta=105.2,124.3
XS Rating Curve= 0 ,0
Exp/Cntr=0.3,0.1

Type RM Length L Ch R = 1 ,5955.4  ,194.7,192.3,189.8
XS GIS Cut Line= 2
     1865304.167      455832.699     1865433.331      456009.795
#Sta/Elev= 26
       0  895.84     9.5  891.26    19.1  886.79    28.6  881.62    38.1  875.53
    47.6   868.6    57.2  861.35    66.7  855.29    69.5  854.86    76.2  853.84
    84.5  853.95    85.8  853.97    95.3  854.54   104.8   855.3   114.4  856.13
   123.9  856.66   133.4  857.15     143  857.63   152.5  858.09     162  858.61
   171.5  859.24   181.1  860.04   190.6  860.93   200.1  861.89   209.7  862.95
   219.2  864.01
#Mann= 3 , 0 , 0
       0      .1       0    69.5    .045       0    84.5      .1       0
Bank Sta=69.5,84.5
XS Rating Curve= 0 ,0
Exp/Cntr=0.3,0.1

Type RM Length L Ch R = 1 ,5763.2  ,240.1,248.1,255.8
XS GIS Cut Line= 2
     1865167.714      455964.005       1865340.5      456152.713
#Sta/Elev= 29
       0  894.64     9.8  891.66    19.7  888.66    29.5  885.65    39.4  882.62
    49.2  879.48      59  875.96    68.9  872.05    78.7  867.87    88.6  863.61
    98.4  859.04   108.2  854.01     114  851.94   118.1  850.48   127.9  849.99
     129  850.18   137.8  851.73   147.6  854.43   157.4  856.64   167.3     858
   177.1  858.77     187  859.26   196.8  859.62   206.7  859.94   216.5  860.18
   226.3  860.45   236.2  860.67     246  860.95   255.9  861.28
#Mann= 3 , 0 , 0
       0      .1       0     114    .045       0     129      .1       0
Bank Sta=114,129
XS Rating Curve= 0 ,0
Exp/Cntr=0.3,0.1

Type RM Length L Ch R = 1 ,5515    ,99.4,71.7,39.7
XS GIS Cut Line= 3
     1864998.158      456066.542     1865007.273      456108.643
     1865081.058      456284.858
#Sta/Elev= 28
       0   871.1     8.6  867.88    17.2  864.62    25.8  861.43    34.5  858.25
    43.1  855.14    52.6  851.35    62.2  846.96    70.5  844.27    71.7  843.88
    81.3   843.2    85.5  843.62    90.8  844.15   100.4  845.87   109.9  847.23
   119.5  848.41     129   849.4   138.6     850   148.2   850.3   157.7  850.44
   167.2  850.49   176.8  850.37   186.4  850.26   195.9  850.22   205.5   850.2
     215  850.34   224.6  850.52   234.1  852.08
#Mann= 3 , 0 , 0
       0      .1       0    71.7    .045       0    90.8      .1       0
Bank Sta=71.7,90.8
XS Rating Curve= 0 ,0
Exp/Cntr=0.3,0.1

Type RM Length L Ch R = 1 ,5443.3  ,53.8,45,45.4
XS GIS Cut Line= 4
     1864879.669      456089.112     1864930.885      456180.288
     1865018.148      456176.726     1865066.073      456289.189
#Sta/Elev= 30
       0  857.81     9.5  855.02      19  852.44    28.5  850.15      38  848.42
    47.5  847.42      57   846.6    66.6  846.24    76.1  846.12    85.6  846.27
    95.1  847.08   104.6  848.09   114.3  846.44     124  843.37   133.7  842.73
   143.4   842.7   153.1  842.98   162.8  844.46   172.5  845.82   182.2  846.82
   191.9  847.48   201.3  848.66   210.7  849.59   220.1  850.19   238.9  850.74
   267.1  850.84   276.6  851.02   295.4  851.66   304.8  852.11   314.2  853.74
#Mann= 3 , 0 , 0
       0      .1       0     124    .045       0   153.1      .1       0
Bank Sta=124,153.1
XS Rating Curve= 0 ,0
Exp/Cntr=0.3,0.1

Type RM Length L Ch R = 1 ,5398.3  ,84.9,129.4,168.5
XS GIS Cut Line= 4
     1864840.283      456101.031     1864904.394      456219.496
     1864996.109      456215.751     1865044.034      456328.214
#Sta/Elev= 29
       0  854.04     9.6   851.1    19.2     849    28.9  847.94    38.5  847.47
    57.7  846.91      77  846.71    86.6  846.72    96.2  846.92   115.5   847.9
   125.1  847.53   134.7  845.53   143.9  845.17   153.1  844.46   162.2  843.42
   171.4  842.73   180.6  842.67   189.8   843.4   208.1  846.91   217.3  848.44
   226.5  849.56   235.9  850.25   273.5  852.62   282.9  853.34   292.3  853.95
   301.7  854.84   311.1   856.8   320.5  859.76   348.7   870.5
#Mann= 3 , 0 , 0
       0      .1       0   162.2    .045       0   189.8      .1       0
Bank Sta=162.2,189.8
XS Rating Curve= 0 ,0
Exp/Cntr=0.3,0.1

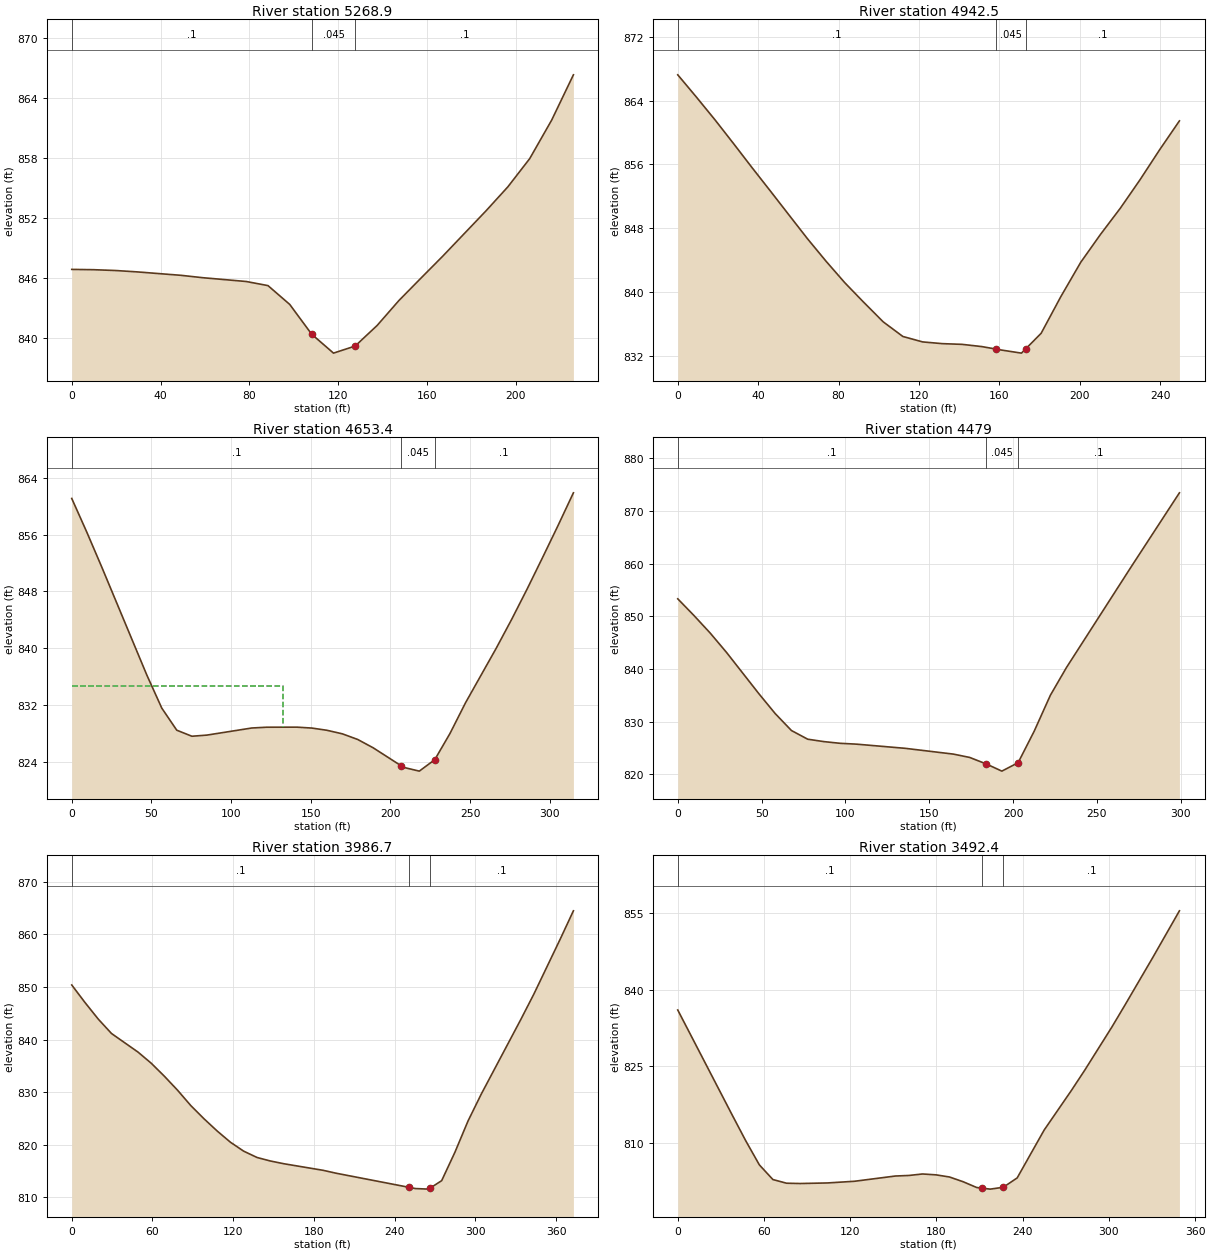
Type RM Length L Ch R = 1 ,5268.9  ,327.8,326.4,324.9
XS GIS Cut Line= 2
     1864816.735      456133.383     1864828.019      456359.077
#Sta/Elev= 26
       0  846.85     9.8  846.82    19.6  846.74    29.5   846.6    39.3  846.43
    49.1  846.26      59  846.02    68.8  845.83    78.6  845.64    88.4  845.23
    98.2  843.35   108.1  840.37   117.3   838.6   117.9  838.48   127.7  839.19
   132.3  840.15   137.6  841.25   147.4  843.74   157.2  845.95     167  848.14
   176.8  850.42   186.7  852.72   196.5  855.11   206.3  857.92   216.2  861.77
     226   866.3
#Mann= 3 , 0 , 0
       0      .1       0   108.1    .045       0   127.7      .1       0
Bank Sta=108.1,127.7
XS Rating Curve= 0 ,0
Exp/Cntr=0.3,0.1

Type RM Length L Ch R = 1 ,4942.5  ,294.1,289.1,283.8
XS GIS Cut Line= 3
     1864451.368      456168.376     1864496.623      456248.836
     1864514.904       456405.11
#Sta/Elev= 29
       0  867.24     9.2  864.47    18.5   861.6    27.7  858.63    36.9  855.61
    46.2  852.62    55.4  849.63    64.6  846.65    73.8  843.84    83.1  841.15
    92.3  838.75   102.2  836.24     112   834.4   121.8  833.72   131.6   833.5
   141.5  833.41   151.3  833.13   158.3  832.82   161.2  832.69     171  832.31
   173.3  832.89   180.8   834.8   190.6   839.4   200.5  843.71   210.3   847.2
   220.2   850.5     230  854.07   239.8  857.85   249.6  861.46
#Mann= 3 , 0 , 0
       0      .1       0   158.3    .045       0   173.3      .1       0
Bank Sta=158.3,173.3
XS Rating Curve= 0 ,0
Exp/Cntr=0.3,0.1

Type RM Length L Ch R = 1 ,4653.4  ,173.2,174.3,175.4
XS GIS Cut Line= 3
     1864171.162      456198.931     1864215.741      456352.714
     1864267.962      456498.274
#Sta/Elev= 28
       0  861.09     9.4  856.37    18.8  851.45    47.1  836.24    56.5  831.58
    65.9  828.47    75.4  827.62    84.8  827.78     113  828.78   122.4  828.89
   141.3   828.9   150.7  828.77   160.1  828.46   169.8  827.96   179.4  827.17
   189.1     826   206.8  823.45   208.4  823.23   218.1  822.71   227.8  824.32
   237.4  828.03   247.1  832.33   266.4  840.02   276.1  844.09   285.8  848.36
   295.4  852.75   305.1  857.25   314.8  861.88
#Mann= 3 , 0 , 0
       0      .1       0   206.8    .045       0   227.8      .1       0
#XS Ineff= 2 , 0
          132.61  834.67
Permanent Ineff=
       F       F
Bank Sta=206.8,227.8
XS Rating Curve= 0 ,0
Exp/Cntr=0.3,0.1

Type RM Length L Ch R = 1 ,4479    ,504.1,492.3,479.8
XS GIS Cut Line= 3
     1863979.756      456298.758     1864051.804      456402.056
     1864102.152      456567.855
#Sta/Elev= 22
       0  853.32     9.7  850.14    19.4   846.8    29.1  843.14    48.4   835.3
    58.1  831.54    67.8  828.32    77.5  826.67    87.2  826.21    96.9  825.89
   106.6  825.73   135.6  824.94   164.4  823.84   174.1  823.21   184.1  821.96
   193.3  820.61     203  822.21   212.6   828.2   222.2  834.99   231.8  840.26
   270.3  859.33   299.2  873.44
#Mann= 3 , 0 , 0
       0      .1       0   184.1    .045       0     203      .1       0
Bank Sta=184.1,203
XS Rating Curve= 0 ,0
Exp/Cntr=0.3,0.1

Type RM Length L Ch R = 1 ,3986.7  ,494.3,494.4,495.5
XS GIS Cut Line= 3
     1863453.473      456465.278     1863569.707      456598.783
     1863714.606      456730.442
#Sta/Elev= 30
       0  850.39     9.8  847.07    19.7   843.9    29.5  841.17    49.2  837.63
      59  835.52    68.8  833.04    78.7  830.35    88.5  827.44    98.3  824.93
   108.2  822.58     118  820.46   127.8  818.77   137.7  817.57   147.5  816.91
   157.4  816.39   186.8  815.13   196.6  814.57   250.9  811.88   255.3  811.66
   265.1  811.55   265.9  811.68   274.9  813.16   284.7  818.54   294.5  824.52
   304.3  829.62   333.6  843.77   343.4  848.65     363  859.12   372.8   864.5
#Mann= 3 , 0 , 0
       0      .1       0   250.9    .045       0   265.9      .1       0
Bank Sta=250.9,265.9
XS Rating Curve= 0 ,0
Exp/Cntr=0.3,0.1

Type RM Length L Ch R = 1 ,3492.4  ,277.8,287.9,296.6
XS GIS Cut Line= 3
     1863139.468      456800.977     1863236.907       456940.67
     1863360.971      457069.409
#Sta/Elev= 27
       0  836.01    37.8  815.46    47.3  810.37    56.8  805.63    66.2  802.76
    75.7  802.04    85.2  801.98   104.1  802.09     123  802.42   151.4  803.45
   160.9  803.56   170.3  803.85   179.7  803.68   189.1  803.26   198.6  802.33
     208   801.2   211.5  801.08   217.4  800.88   226.5  801.24   236.2  803.08
     255  812.48   273.8  820.18   283.2   824.2   302.1  832.67   311.5  837.12
   330.3  846.18   349.1  855.46
#Mann= 3 , 0 , 0
       0      .1       0   211.5    .045       0   226.5      .1       0
Bank Sta=211.5,226.5
XS Rating Curve= 0 ,0
Exp/Cntr=0.3,0.1

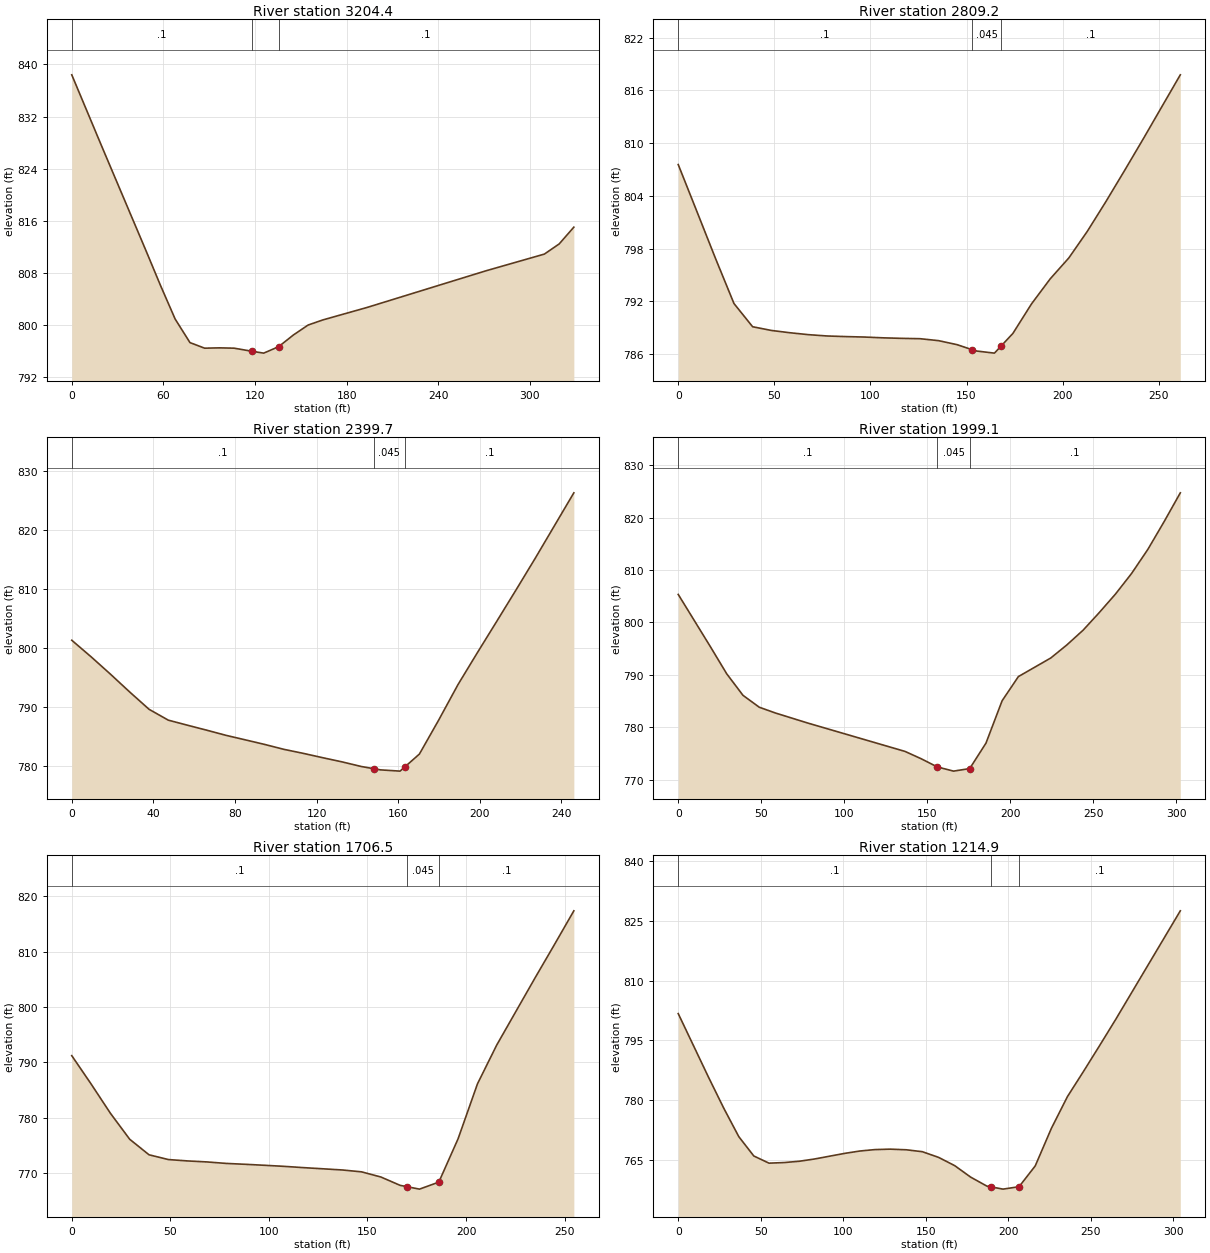
Type RM Length L Ch R = 1 ,3204.4  ,393,395.2,397.3
XS GIS Cut Line= 2
     1862937.362      456887.326     1863062.505      457191.423
#Sta/Elev= 20
       0  838.41    19.3  827.61    48.4   811.5      58   806.1    67.7  800.88
    77.4  797.26      87   796.4    96.7  796.45   106.4   796.4   118.3  795.91
   125.7  795.64   135.4  796.62   145.1  798.42   154.8  799.96   164.4  800.74
   193.4  802.66   270.8  808.26   309.5  810.86   319.2  812.42   328.8     815
#Mann= 3 , 0 , 0
       0      .1       0   118.3    .045       0   135.4      .1       0
Bank Sta=118.3,135.4
XS Rating Curve= 0 ,0
Exp/Cntr=0.3,0.1

Type RM Length L Ch R = 1 ,2809.2  ,401.8,409.5,416.8
XS GIS Cut Line= 2
      1862600.89      457049.064     1862676.585      457299.064
#Sta/Elev= 30
       0  807.56     9.7  802.23    19.4  796.88      29  791.76    38.7  789.12
    48.4   788.7      58  788.44    67.7  788.22    77.4  788.07    87.1     788
    96.7  787.95   106.4  787.86   116.1   787.8   125.8  787.76   135.4  787.54
   145.1  787.08   152.9  786.51   154.8  786.37   164.5  786.12   167.9  786.91
   174.1  788.36   183.8  791.72   193.5  794.56   203.2  796.94   212.8  799.96
   222.5  803.35   232.2  806.88   241.9  810.47   251.5   814.1   261.2  817.76
#Mann= 3 , 0 , 0
       0      .1       0   152.9    .045       0   167.9      .1       0
Bank Sta=152.9,167.9
XS Rating Curve= 0 ,0
Exp/Cntr=0.3,0.1

Type RM Length L Ch R = 1 ,2399.7  ,392.1,400.6,407.9
XS GIS Cut Line= 2
      1862253.78      457109.412     1862245.917      457355.383
#Sta/Elev= 29
       0  801.31     9.5  798.49    18.9  795.57    28.4  792.52    37.9  789.58
    47.3  787.74    56.8  786.87    66.3  786.02    75.7  785.15    85.2  784.38
    94.6  783.61   104.1  782.77   113.6  782.09     123  781.36   132.5  780.65
     142  779.86   148.2  779.48   151.4  779.29   160.9  779.08   163.2  779.78
   170.4  781.98   179.8  787.72   189.3  793.77   198.8  799.19   208.2  804.46
   217.7  809.82   227.2  815.25   236.6  820.77   246.1  826.35
#Mann= 3 , 0 , 0
       0      .1       0   148.2    .045       0   163.2      .1       0
Bank Sta=148.2,163.2
XS Rating Curve= 0 ,0
Exp/Cntr=0.3,0.1

Type RM Length L Ch R = 1 ,1999.1  ,290.8,292.6,293.9
XS GIS Cut Line= 2
     1861937.696      457006.703     1861828.668      457288.647
#Sta/Elev= 24
       0  805.35    19.5   795.3    29.2  790.19      39  786.08    48.8  783.81
    58.5  782.71      78  780.79   136.5  775.38   146.3  773.97     156  772.41
   165.8  771.61   175.5   772.1   185.3  776.96     195  785.04   204.8  789.66
   224.3  793.21     234  795.71   243.8  798.53   253.5  801.88   263.3  805.43
     273  809.37   282.8  813.97   292.5  819.22   302.3  824.75
#Mann= 3 , 0 , 0
       0      .1       0     156    .045       0   175.5      .1       0
Bank Sta=156,175.5
XS Rating Curve= 0 ,0
Exp/Cntr=0.3,0.1

Type RM Length L Ch R = 1 ,1706.5  ,493.3,491.6,489.9
XS GIS Cut Line= 2
     1861668.946      456946.286     1861560.612      457176.842
#Sta/Elev= 29
       0  791.21     9.8   786.1    19.6  780.81    29.4  776.11    39.2  773.31
      49  772.45    58.8   772.2    68.6  772.02    78.4  771.75    88.2  771.59
      98  771.41   107.8  771.22   117.6  770.99   127.4  770.78   137.2  770.57
     147  770.23   156.8   769.3   166.6  767.79   170.1  767.55   176.4  767.11
   185.1  768.23   186.2  768.37     196  776.22   205.8  786.11   215.6  793.14
   225.4  799.25   235.1   805.3   244.9  811.29   254.7  817.36
#Mann= 3 , 0 , 0
       0      .1       0   170.1    .045       0   186.2      .1       0
Bank Sta=170.1,186.2
XS Rating Curve= 0 ,0
Exp/Cntr=0.3,0.1

Type RM Length L Ch R = 1 ,1214.9  ,364.4,364.5,364.3
XS GIS Cut Line= 3
      1861213.39      456744.203     1861161.587      456861.671
     1861098.878      457025.949
#Sta/Elev= 29
       0  801.72    18.3  785.77    27.5  778.01    36.7  770.78    45.8  765.92
      55  764.12    64.2  764.27    73.4   764.6    82.5  765.16   100.9  766.58
     110  767.17   119.2  767.53   128.4  767.64   138.2  767.48   147.9     767
   157.7  765.58   167.5   763.5   177.2   760.6     187  758.35   189.8  758.13
   196.8  757.59   206.5   758.2   216.3  763.43   226.1  772.88   235.8  780.84
   245.6  787.22   255.4  793.74   265.2  800.36   304.2  827.56
#Mann= 3 , 0 , 0
       0      .1       0   189.8    .045       0   206.5      .1       0
Bank Sta=189.8,206.5
XS Rating Curve= 0 ,0
Exp/Cntr=0.3,0.1

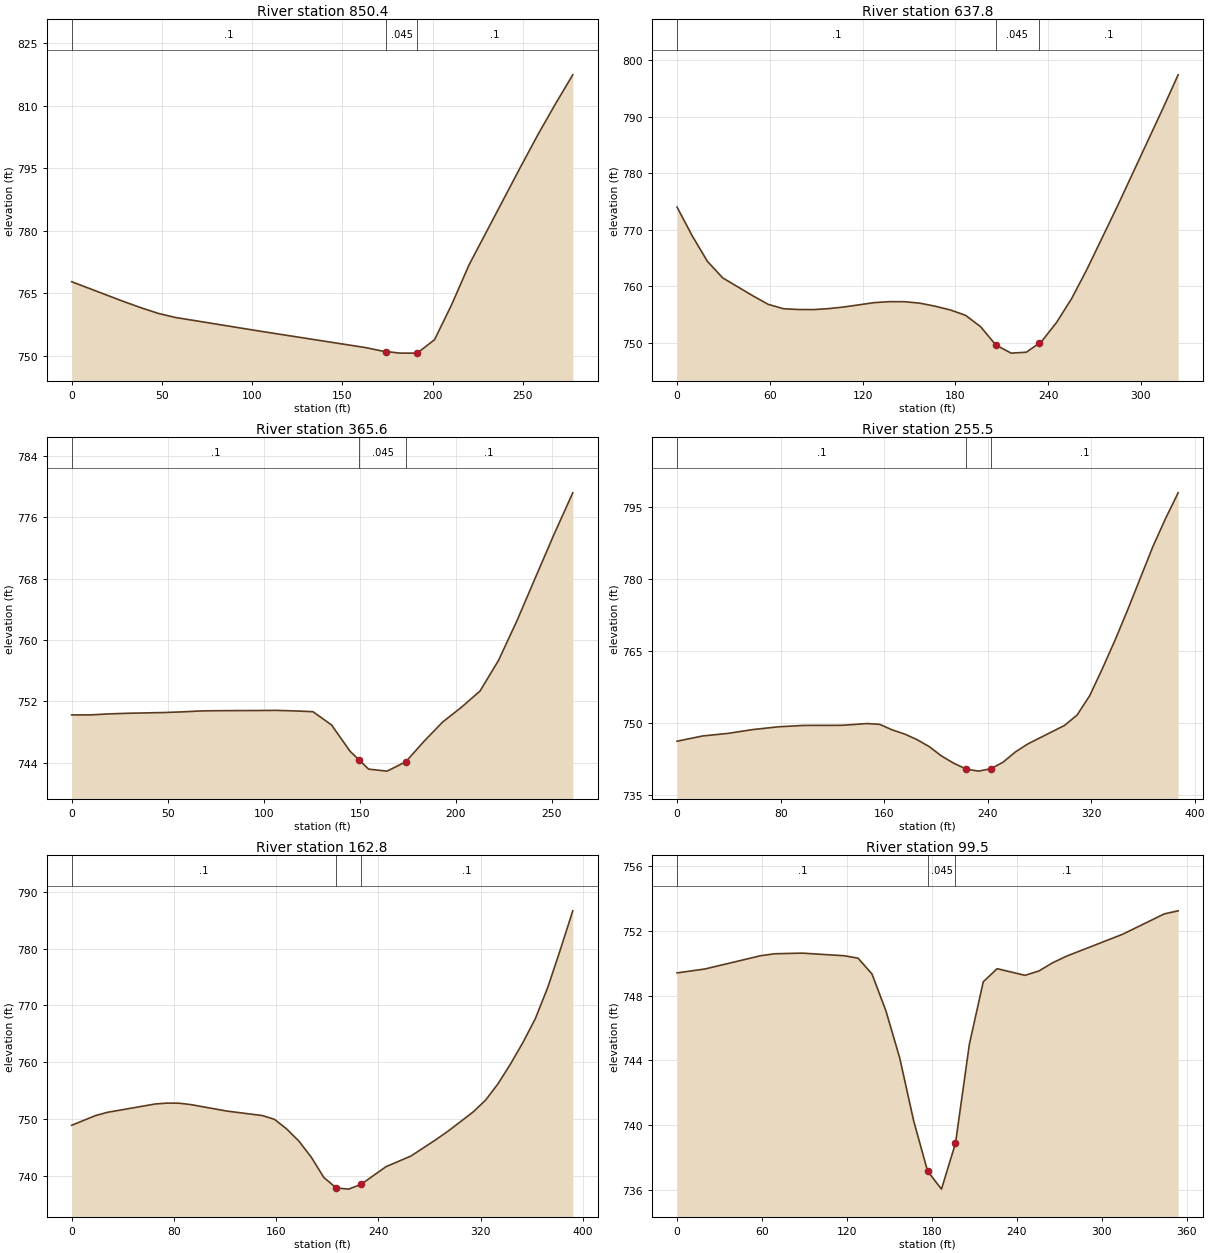
Type RM Length L Ch R = 1 ,850.4   ,211,212.7,214.1
XS GIS Cut Line= 2
     1860866.777      456618.924     1860768.015      456878.426
#Sta/Elev= 18
       0   767.8    28.7  763.07    38.3  761.58    47.9  760.22    57.4  759.24
   105.3  755.89   162.8  752.02   172.3  751.17   174.2  751.08   181.9  750.69
   191.5  750.69   201.1  753.92   210.6  762.33   220.2  771.83   248.9  795.42
   258.5  803.13   268.1  810.42   277.7  817.38
#Mann= 3 , 0 , 0
       0      .1       0   174.2    .045       0   191.5      .1       0
Bank Sta=174.2,191.5
XS Rating Curve= 0 ,0
Exp/Cntr=0.3,0.1

Type RM Length L Ch R = 1 ,637.8   ,272.9,272.2,271.4
XS GIS Cut Line= 2
     1860692.918      456532.389     1860557.501      456826.834
#Sta/Elev= 30
       0  774.01     9.8  768.94    19.6  764.45    29.5  761.52    49.1  758.34
    58.9  756.85    68.8  756.07    78.6  755.93    88.4  755.92    98.2  756.09
     108  756.38   127.7  757.15   137.5  757.32   147.3  757.31   157.1  757.05
     167  756.51   176.8  755.85   186.6  754.91   196.4  752.88   206.2  749.66
   216.1  748.23   225.9  748.39     234  749.94   235.7  750.26   245.5  753.66
   255.3   757.9   265.2  763.07   284.8  774.16   314.3  791.46   324.1  797.37
#Mann= 3 , 0 , 0
       0      .1       0   206.2    .045       0     234      .1       0
Bank Sta=206.2,234
XS Rating Curve= 0 ,0
Exp/Cntr=0.3,0.1

Type RM Length L Ch R = 1 ,365.6   ,135.7,110.1,85.5
XS GIS Cut Line= 2
     1860430.931      456455.973     1860329.723        456696.4
#Sta/Elev= 30
       0  750.23     9.7  750.23    19.3  750.36      29  750.44    38.6  750.49
    48.3  750.54      58  750.63    67.6  750.75    77.3  750.78      87  750.79
    96.6   750.8   106.3  750.82   115.9  750.75   125.6  750.65   135.3  748.92
   144.9   745.5   149.7  744.34   154.6  743.16   164.2   742.9   164.7  742.96
   173.9  744.11   183.6  746.83   193.2  749.31   202.9  751.22   212.6  753.34
   222.2  757.32   231.9  762.54   241.5  768.16   251.2   773.8   260.9  779.18
#Mann= 3 , 0 , 0
       0      .1       0   149.7    .045       0   173.9      .1       0
Bank Sta=149.7,173.9
XS Rating Curve= 0 ,0
Exp/Cntr=0.3,0.1

Type RM Length L Ch R = 1 ,255.5   ,89,92.6,95.5
XS GIS Cut Line= 4
     1860260.973      456354.611     1860231.592      456518.282
     1860293.269      456635.986     1860307.391      456722.534
#Sta/Elev= 30
       0  746.16    19.6  747.25    39.1  747.79    58.7   748.6    78.2  749.17
    97.8  749.46   127.2  749.48   146.7  749.85   156.5  749.68   166.3  748.51
   175.8  747.65   185.3  746.49   194.8  745.02   204.2  743.07   213.8  741.54
   223.2  740.35   232.7  739.91   242.3  740.41   251.7  741.77   261.2  743.91
   270.7  745.57   299.2  749.46   308.9  751.63   318.7  755.71   328.4  761.32
   338.2  767.28   347.9  773.58   367.4  786.82   377.1  792.64   386.9  798.06
#Mann= 3 , 0 , 0
       0      .1       0   223.2    .045       0   242.3      .1       0
Bank Sta=223.2,242.3
XS Rating Curve= 0 ,0
Exp/Cntr=0.3,0.1

Type RM Length L Ch R = 1 ,162.8   ,54.2,63.4,72.5
XS GIS Cut Line= 3
     1860148.473      456342.806     1860152.277      456510.754
     1860256.226      456709.127
#Sta/Elev= 30
       0  748.92    18.7  750.63      28   751.2    65.3  752.66    74.7  752.82
      84   752.8    93.3  752.55   121.3  751.42   149.3  750.62   158.7  749.95
     168  748.31   177.7  746.15   187.5  743.28   197.2  739.75   206.9   737.9
   216.7  737.69   226.4  738.54   245.9  741.64   265.4  743.51   284.8  746.37
   294.6  747.91     314  751.25   323.8  753.34   333.5  756.21   343.3   759.7
     353  763.47   362.7  767.67   372.5   773.2   382.2  779.76     392  786.63
#Mann= 3 , 0 , 0
       0      .1       0   206.9    .045       0   226.4      .1       0
Bank Sta=206.9,226.4
XS Rating Curve= 0 ,0
Exp/Cntr=0.3,0.1

Type RM Length L Ch R = 1 ,99.5    ,97.4,99.5,101.5
XS GIS Cut Line= 2
     1860081.218      456366.644     1860137.762      456715.881
#Sta/Elev= 24
       0   749.4    19.6  749.64      59  750.46    68.8  750.58    88.4  750.62
   117.9  750.46   127.8  750.31   137.6  749.34   147.4  747.08   157.2  744.16
   167.1  740.26   176.9  737.17   186.7  736.06   196.6  738.89   206.4     745
   216.2  748.85     226  749.66   245.7  749.25   255.5  749.52   265.3  750.03
   275.2  750.44   314.5  751.78     344  753.04   353.8  753.23
#Mann= 3 , 0 , 0
       0      .1       0   176.9    .045       0   196.6      .1       0
Bank Sta=176.9,196.6
XS Rating Curve= 0 ,0
Exp/Cntr=0.3,0.1

Chan Stop Cuts=-1
Use User Specified Reach Order=0
Composite Channel Slope=5